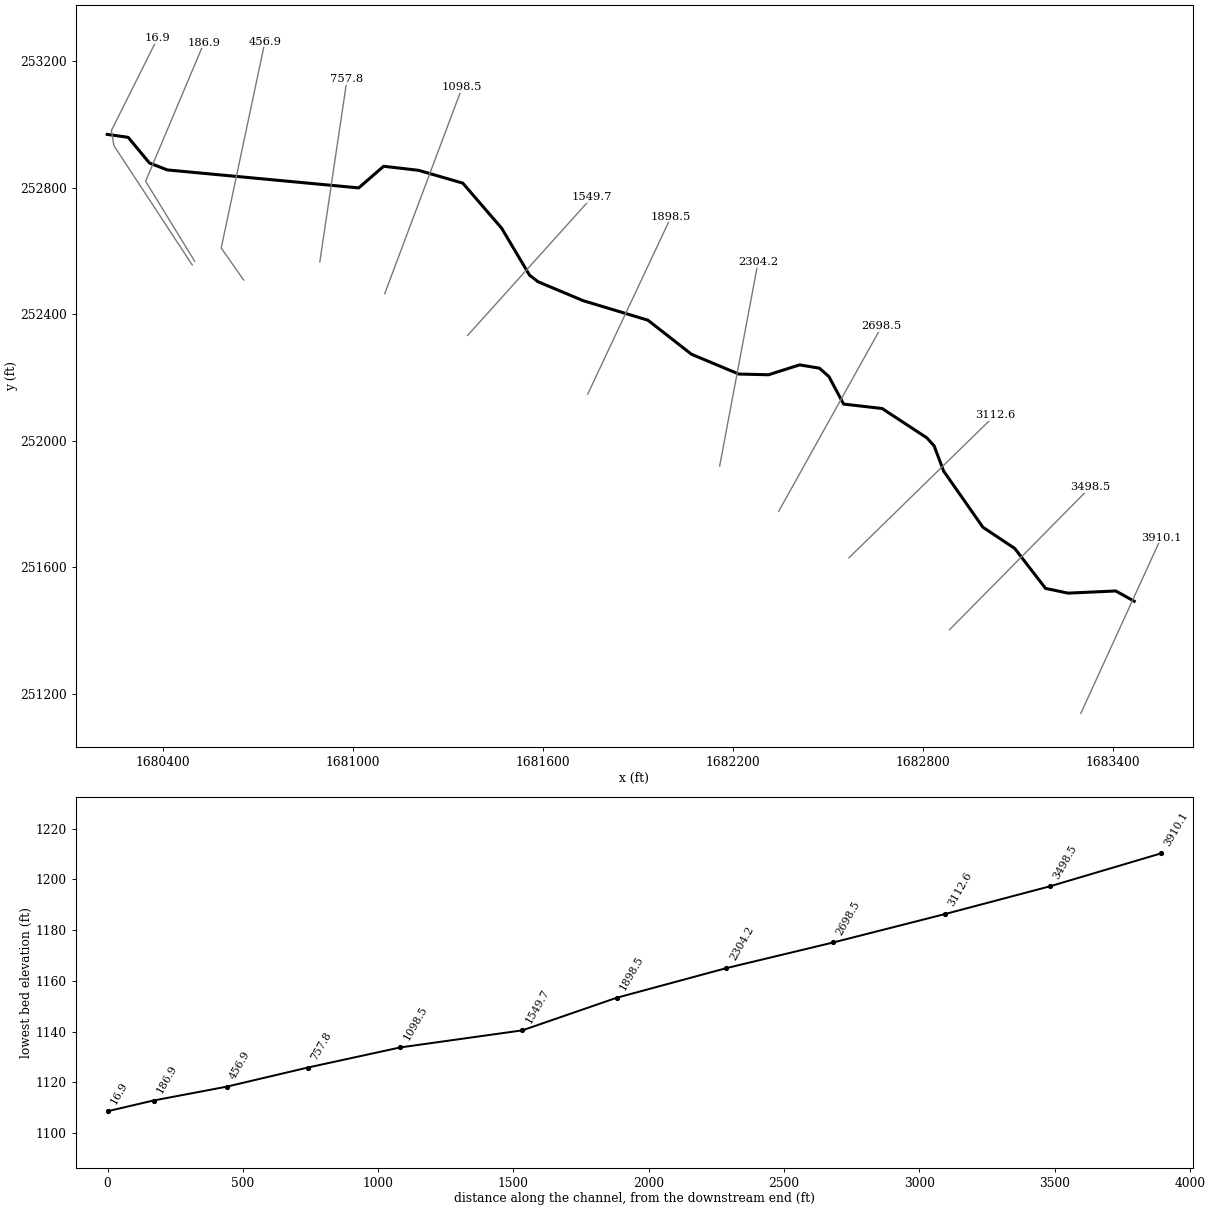
--- LEFTFRK.prj (project) ---

Proj Title=LEFTFRK
Current Plan=p01
Default Exp/Contr=0,0
English Units
Geom File=g01
Flow File=f01
Plan File=p01
BEGIN DESCRIPTION:
END DESCRIPTION:
DSS Export Rating Curves= 0
DSS Export Rating Curve Sorted= 0
DSS Export Volume Flow Curves= 0
DXF OffsetX= 0
DXF OffsetY= 0
DXF ScaleX= 0
DXF ScaleY= 0

--- LEFTFRK.p01 (plan) ---

Plan Title=Floodplain
Program Version=4.00
Geom File=g01
Flow File=f01
K Sum by GR=0
Std Step Tol=0.01
Critical Tol=0.01
Num of Std Step Trials=20
Max Error Tol=0.3
Flow Tol Ratio=0.001
Split Flow NTrial=30
Split Flow Tol=0.02
Split Flow Ratio=0.02
Log Output Level=0
Friction Slope Method=1
Unsteady Friction Slope Method=2
Unsteady Bridges Friction Slope Method=1
Global Log Level=0
CheckData=False
Run HTab=0
Run UNet=0
Run PostProcess=0
UNET Theta=0
UNET Theta Warmup=0
UNET ZTol=0
UNET ZSATol=0
UNET MxIter=0
UNET MaxInSteps=0
UNET DtIC=0
UNET DtMin=0
UNET MaxCRTS=0
UNET WFStab=0
UNET SFStab=0
UNET WFX=0
UNET SFX=0
UNET DSS MLevel=0
UNET DZMax Abort=0
UNET Convert EG Bridges=0
UNET Use Existing IB Tables=0
UNET Froude Limit=0
UNET Froude Power=0
Write IC File=0
Echo Input=False
Echo Output=False
Write Detailed=0

--- LEFTFRK.f01 (steady flow) ---

Flow Title=NFF Regression Equation
Program Version=4.00
Number of Profiles=1
Profile Names=P100yr
River Rch & RM=LEFTFRK,Main      ,3910.1
882.6886
River Rch & RM=LEFTFRK,Main      ,3112.6
909.5346
River Rch & RM=LEFTFRK,Main      ,186.9
985.0382
Boundary for River Rch & Prof#=LEFTFRK,Main      ,1
Up Type=0
Dn Type=3
Dn Slope=0.022118

--- LEFTFRK.g01 (geometry) ---

Geom Title=USGS 10m DEM
Program Version=4.10

River Reach=LEFTFRK         ,Main
Reach XY= 30
      1683468.13      251493.053     1683409.685      251525.496
     1683258.852      251518.642     1683187.845       251533.59
     1683090.556      251659.835     1682989.792       251727.01
     1682865.864      251904.216     1682835.751      251984.132
     1682812.587      252009.612     1682671.286      252102.268
     1682549.675      252116.167     1682503.347      252203.032
     1682473.233      252229.671      1682410.69      252240.095
     1682312.243      252208.823     1682218.429      252211.139
     1682069.021      252273.682     1681931.194      252381.395
     1681727.351       252442.78     1681583.733      252503.006
     1681557.095      252523.854     1681469.071      252672.104
     1681346.302      252814.563     1681206.159        252855.1
      1681096.13       252867.84     1681017.372      252799.507
      1680412.79      252856.258     1680356.038      252878.264
     1680288.862      252959.339     1680222.758      252968.589

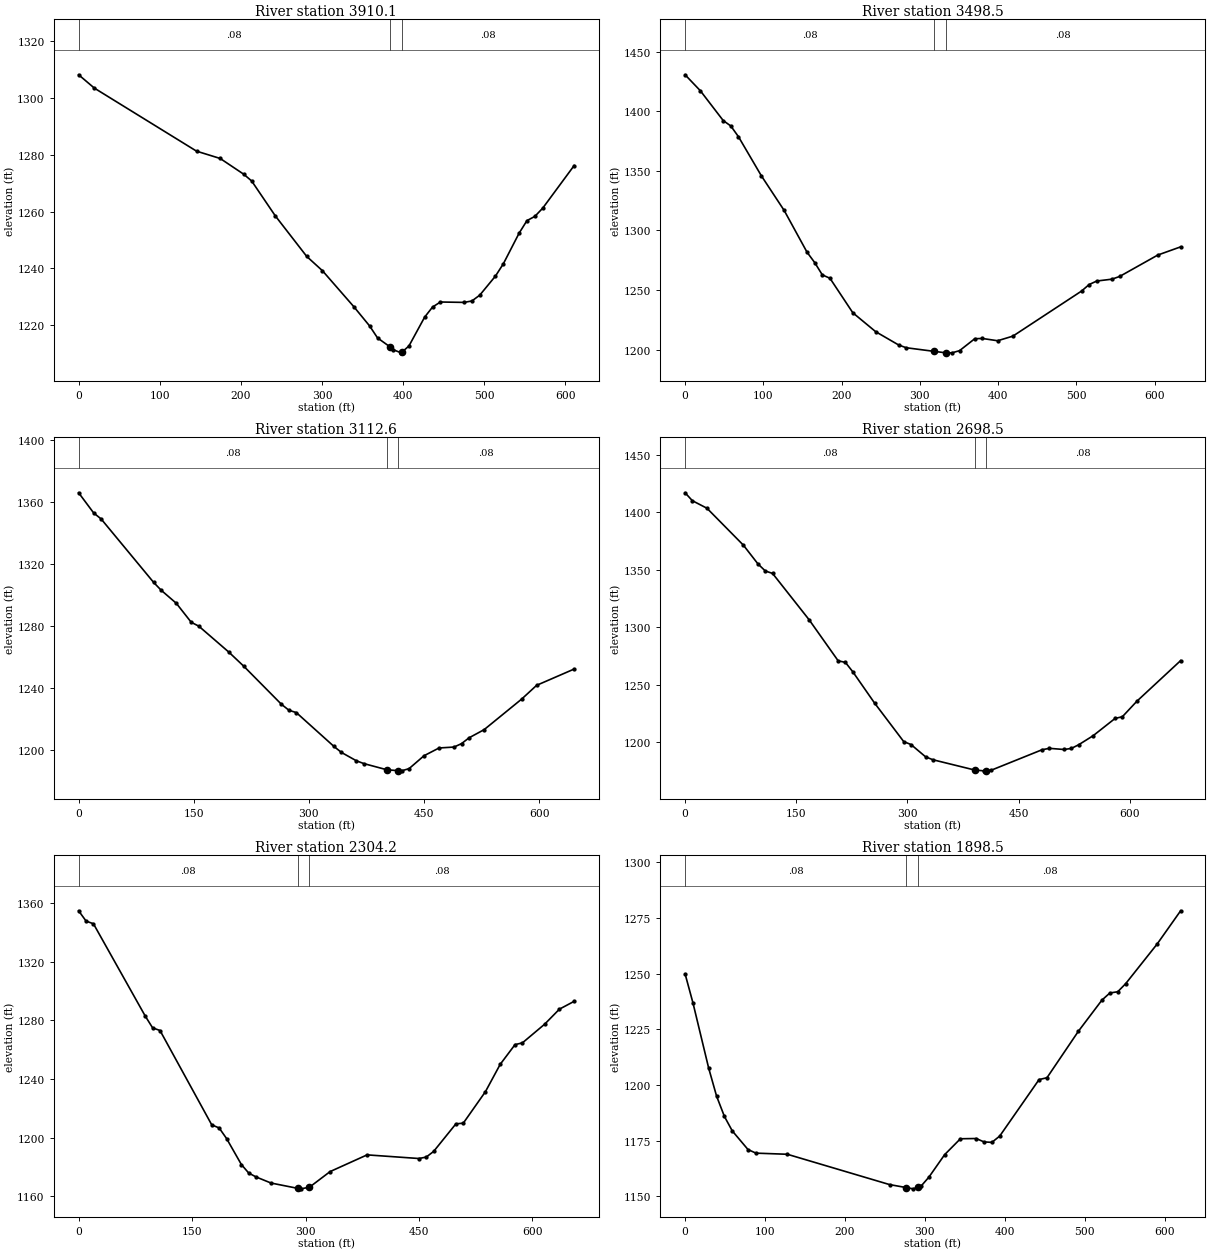
Type RM Length L Ch R = 1 ,3910.1  ,419.8,411.6,403.5
XS GIS Cut Line= 2
     1683299.337      251138.581     1683553.396      251694.126
#Sta/Elev= 30
       0 1308.19    19.4 1303.49   145.4 1281.29   174.5 1278.72   203.6 1273.16
   213.3  1270.8   242.4 1258.53   281.2 1244.23   300.6 1239.19   339.4 1226.48
   358.8 1219.72   368.5 1215.53   383.3  1212.5   387.9 1211.38   397.6 1210.28
   398.3 1210.46   407.2 1212.69   426.6 1222.87   436.3  1226.4     446 1228.18
   475.1 1228.04   484.8 1228.54   494.5 1230.59   513.9 1237.32   523.6 1241.64
     543 1252.41   552.7 1256.84   562.4 1258.32   572.1 1261.22   610.9 1276.24
#Mann= 3 , 0 , 0
       0     .08       0   383.3    .045       0   398.3     .08       0
Bank Sta=383.3,398.3
XS Rating Curve= 0 ,0
Exp/Cntr=0.3,0.1

Type RM Length L Ch R = 1 ,3498.5  ,386.2,385.9,385.6
XS GIS Cut Line= 2
     1682884.483      251403.075      1683329.29      251853.564
#Sta/Elev= 30
       0 1430.65    19.5 1417.24    48.7 1392.23    58.4 1387.68    68.2 1378.65
    97.4 1345.89   126.6 1316.76   155.8 1281.72   165.6 1273.01   175.3 1262.72
   185.1 1259.84   214.3 1230.89   243.5 1215.02   272.7 1203.91   282.4 1201.56
   317.8 1198.54   332.8 1197.31   340.9 1197.27   350.6 1199.08   370.1 1209.13
   379.8 1209.33   399.3 1207.42   418.8  1211.3   506.5 1249.12   516.2  1254.6
     526 1257.56   545.4  1259.1   555.2 1261.39   603.9 1279.35   633.1 1286.22
#Mann= 3 , 0 , 0
       0     .08       0   317.8    .045       0   332.8     .08       0
Bank Sta=317.8,332.8
XS Rating Curve= 0 ,0
Exp/Cntr=0.3,0.1

Type RM Length L Ch R = 1 ,3112.6  ,408,414.1,423.5
XS GIS Cut Line= 2
     1682566.584      251630.271     1683028.384      252081.327
#Sta/Elev= 30
       0 1365.99    19.6 1352.95    29.3 1349.09    97.8 1308.04   107.6    1303
   127.2 1294.63   146.7 1282.33   156.5 1279.85   195.6  1263.1   215.2 1253.91
   264.1  1229.4   273.9 1225.53   283.6 1223.99   332.6 1202.14   342.3 1198.28
   361.9 1192.85   371.7 1191.04   401.6 1187.06   416.6 1186.48   420.6 1186.38
   430.4 1187.79   449.9 1196.13   469.5 1201.15     489 1201.74   498.8 1203.97
   508.6 1207.72   528.2 1212.98   577.1 1232.73   596.6 1241.62   645.5 1252.14
#Mann= 3 , 0 , 0
       0     .08       0   401.6    .045       0   416.6     .08       0
Bank Sta=401.6,416.6
XS Rating Curve= 0 ,0
Exp/Cntr=0.3,0.1

Type RM Length L Ch R = 1 ,2698.5  ,387.2,394.2,398.1
XS GIS Cut Line= 2
     1682344.649      251777.315     1682669.839       252361.52
#Sta/Elev= 30
       0 1417.08     9.8 1410.19    29.5 1403.63    78.7 1371.46    98.3 1355.19
   108.2 1349.06     118 1346.92   167.2 1306.71   206.5  1270.9   216.3  1269.5
   226.2  1261.4   255.6 1234.16     295 1200.57   304.8 1198.04   324.5 1187.33
   334.3 1184.81   390.7 1175.86   403.1 1175.15   405.7 1175.28     413 1175.68
   481.8 1193.55   491.6 1194.72   511.3 1193.72   521.1 1194.65     531 1197.83
   550.6 1205.74   580.1 1220.73     590 1222.24   609.6 1235.75   668.6 1271.06
#Mann= 3 , 0 , 0
       0     .08       0   390.7    .045       0   405.7     .08       0
Bank Sta=390.7,405.7
XS Rating Curve= 0 ,0
Exp/Cntr=0.3,0.1

Type RM Length L Ch R = 1 ,2304.2  ,411.6,405.8,400
XS GIS Cut Line= 2
     1682158.085      251920.663     1682279.366      252564.593
#Sta/Elev= 30
       0 1354.74     9.8 1347.74    19.6 1345.86      88 1282.98    97.8 1274.89
   107.6 1273.06     176 1208.71   185.8 1206.58   195.6 1199.37   215.2 1181.62
   224.9 1175.82   234.7 1173.14   254.3 1169.02   290.1 1165.34   293.4 1165.05
   305.1 1166.12   332.5 1176.82   381.4 1188.22   449.9 1185.74   459.6 1186.72
   469.4 1190.58   498.8 1209.37   508.6 1209.86   537.9 1231.36   557.4 1249.99
     577 1263.44   586.8 1264.64   616.1 1277.34   635.7 1287.63   655.2 1292.98
#Mann= 3 , 0 , 0
       0     .08       0   290.1    .045       0   305.1     .08       0
Bank Sta=290.1,305.1
XS Rating Curve= 0 ,0
Exp/Cntr=0.3,0.1

Type RM Length L Ch R = 1 ,1898.5  ,355.2,348.8,342.4
XS GIS Cut Line= 2
     1681741.043      252147.442     1682004.706      252708.523
#Sta/Elev= 30
       0 1249.92     9.8 1236.94    29.5 1207.57    39.4 1194.99    49.2 1185.86
      59 1179.39    78.7    1171    88.6 1169.39   127.9 1168.88   255.8 1155.26
   276.6 1153.92   285.4 1153.35   291.6 1154.13   295.2 1154.59     305 1158.61
   324.7 1168.72   344.4 1175.85   364.1 1175.96   373.9 1174.44   383.8 1174.23
   393.6 1177.07   442.8 1202.44   452.7 1203.27     492 1224.16   521.5 1238.17
   531.4 1241.35   541.2  1241.9   551.1 1245.52   590.4 1263.29   619.9 1278.28
#Mann= 3 , 0 , 0
       0     .08       0   276.6    .045       0   291.6     .08       0
Bank Sta=276.6,291.6
XS Rating Curve= 0 ,0
Exp/Cntr=0.3,0.1

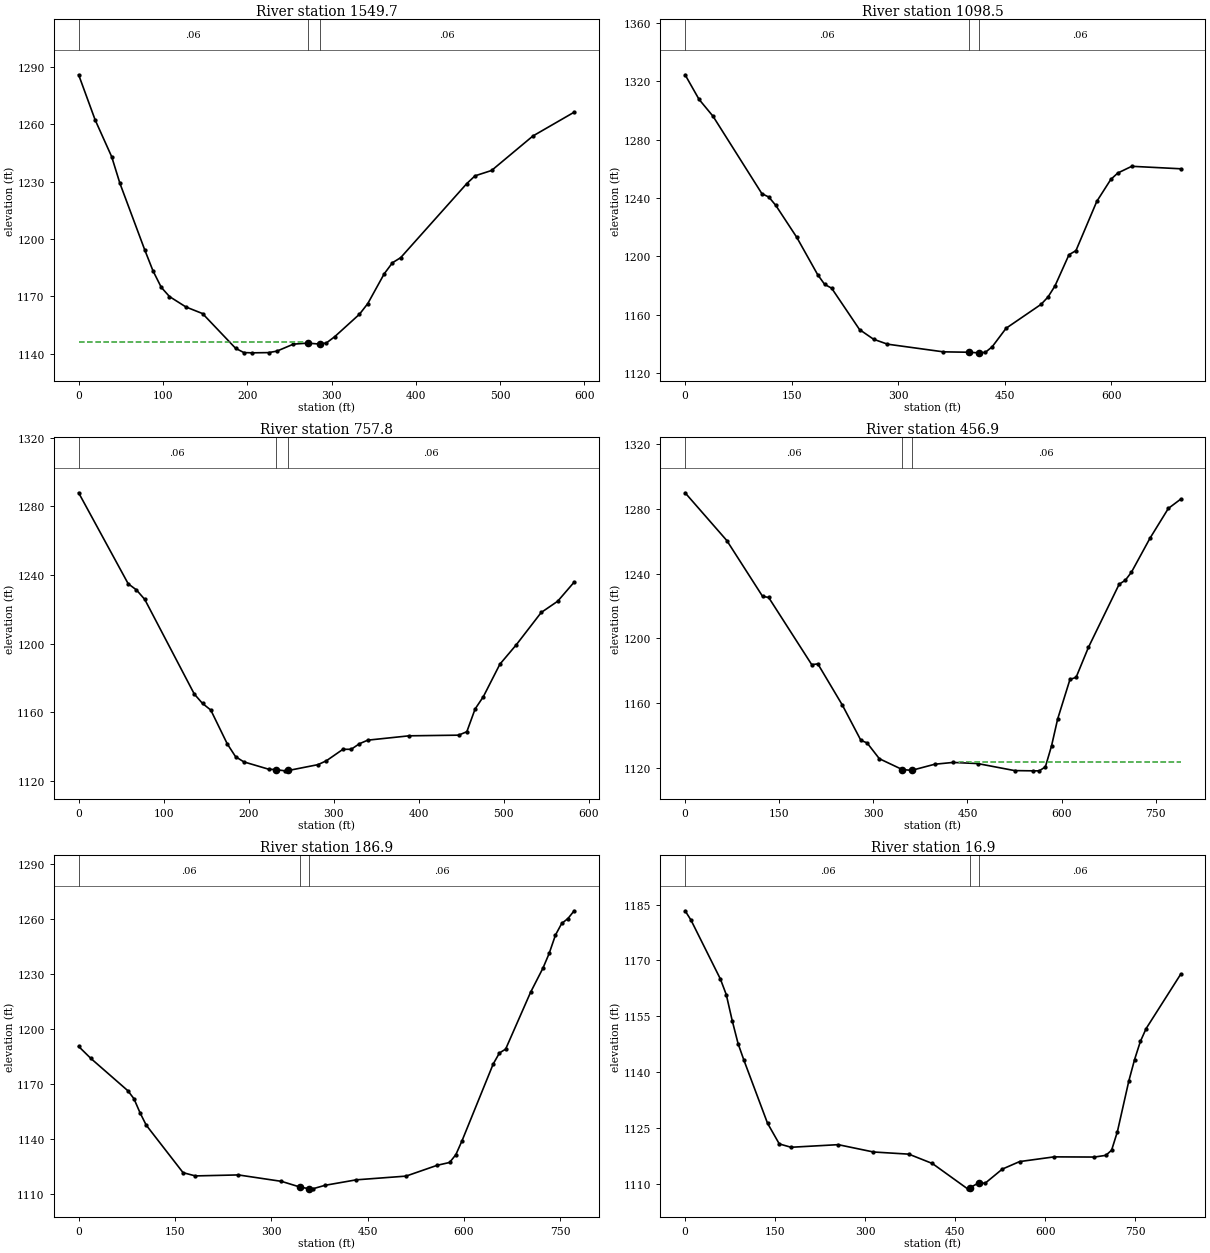
Type RM Length L Ch R = 1 ,1549.7  ,443.1,451.2,459.3
XS GIS Cut Line= 2
     1681361.557      252333.135     1681754.789      252770.177
#Sta/Elev= 30
       0 1285.83    19.6 1262.23    39.2 1243.02      49 1229.06    78.4 1194.34
    88.2 1183.38      98 1174.76   107.8 1169.91   127.4 1164.45     147 1161.03
   186.2 1142.88     196 1140.64   205.8  1140.5   225.4 1140.62   235.2 1141.39
   254.8 1145.04   271.6 1145.58   286.6 1145.06     294  1145.7   303.8 1148.94
   333.2 1160.69     343 1166.22   362.5 1181.78   372.3 1187.58   382.1 1190.26
   460.5 1228.96   470.3 1233.02   489.9 1235.81   538.9 1253.82   587.9 1266.28
#Mann= 3 , 0 , 0
       0     .06       0   271.6    .045       0   286.6     .06       0
#XS Ineff= 2 , 0
          267.85 1145.91
Permanent Ineff=
       F       F
Bank Sta=271.6,286.6
XS Rating Curve= 0 ,0
Exp/Cntr=0.3,0.1

Type RM Length L Ch R = 1 ,1098.5  ,334.9,340.7,346.4
XS GIS Cut Line= 2
     1681099.613      252465.273     1681344.757      253118.325
#Sta/Elev= 30
       0  1324.6    19.6 1307.75    39.3 1296.15   108.1 1243.01   117.9 1240.68
   127.7 1234.95   157.2 1213.04   186.7 1187.35   196.5 1180.74   206.3 1178.14
   245.6 1149.72   265.3 1143.11   284.9 1139.72   363.5 1134.46   399.3 1134.18
   412.6 1133.77   414.3 1133.82   422.5 1134.03   432.3 1137.93   451.9 1150.65
   501.1 1167.04   510.9  1172.1   520.7 1179.67   540.4 1201.09   550.2  1203.9
   579.6 1237.75   599.3 1252.79   609.1 1257.17   628.8 1261.79   697.6 1260.09
#Mann= 3 , 0 , 0
       0     .06       0   399.3    .045       0   414.3     .06       0
Bank Sta=399.3,414.3
XS Rating Curve= 0 ,0
Exp/Cntr=0.3,0.1

Type RM Length L Ch R = 1 ,757.8   ,302.2,300.9,299.5
XS GIS Cut Line= 2
     1680894.496        252565.7     1680980.316      253142.491
#Sta/Elev= 30
       0 1287.83    58.3 1234.84      68 1231.25    77.8 1225.72   136.1 1170.58
   145.8  1165.1   155.5 1161.26   174.9 1141.56   184.7 1134.08   194.4 1131.07
   223.5 1126.81   231.8 1126.57     243 1125.85   246.8 1126.05   281.8 1129.47
   291.6 1131.74     311 1138.39   320.7 1138.41   330.4 1141.63   340.2 1143.72
   388.8 1146.25   447.1 1146.63   456.8 1148.64   466.5 1161.86   476.2 1169.04
   495.7 1187.98   515.1 1199.35   544.3 1218.09   563.7 1224.65   583.1 1235.79
#Mann= 3 , 0 , 0
       0     .06       0   231.8    .045       0   246.8     .06       0
Bank Sta=231.8,246.8
XS Rating Curve= 0 ,0
Exp/Cntr=0.3,0.1

Type RM Length L Ch R = 1 ,456.9   ,274.4,270,265.6
XS GIS Cut Line= 3
     1680653.693      252508.426     1680582.898      252609.562
      1680721.06      253261.419
#Sta/Elev= 30
       0 1289.79    66.5 1260.32   123.4 1225.96   133.2 1225.21   201.8 1183.81
   211.6 1184.24   250.8 1158.73   280.2 1137.08     290 1135.54   309.6 1125.77
   346.2 1119.07   361.2 1118.59   397.8 1122.36   427.2 1123.48   466.4 1122.77
   525.2 1118.44   554.6 1118.29   564.4 1118.29   574.2 1120.73     584 1133.61
   593.8 1150.29   613.4 1174.66   623.2 1175.96   642.8 1194.41   691.8 1233.38
   701.6 1235.84   711.4 1240.81   740.8 1261.67   770.2 1280.14   789.8 1285.83
#Mann= 3 , 0 , 0
       0     .06       0   346.2    .045       0   361.2     .06       0
#XS Ineff= 2 , 0
                           437.2         1123.48
Permanent Ineff=
       F       F
Bank Sta=346.2,361.2
XS Rating Curve= 0 ,0
Exp/Cntr=0.3,0.1

Type RM Length L Ch R = 1 ,186.9   ,156.8,170,179.3
XS GIS Cut Line= 3
     1680499.011      252567.772     1680343.959       252820.41
      1680528.49      253258.169
#Sta/Elev= 30
       0 1190.52    19.1 1183.95    76.5  1166.4    86.1 1162.02    95.6 1154.33
   105.2  1147.6   162.6 1121.66   181.7 1119.89   248.6 1120.43   315.8 1116.92
   344.4 1113.84   359.4 1112.85   364.3 1112.84   383.7 1114.77   432.2 1117.75
   509.7 1119.78   558.2 1125.68   577.6 1127.23   587.3 1131.49     597 1139.15
   645.4 1180.91   655.1 1186.92   664.8 1189.06   703.6 1220.02     723  1233.3
   732.7 1241.37   742.4  1251.3   752.1 1257.59   761.8 1260.28   771.5 1264.51
#Mann= 3 , 0 , 0
       0     .06       0   344.4    .045       0   359.4     .06       0
Bank Sta=344.4,359.4
XS Rating Curve= 0 ,0
Exp/Cntr=0.3,0.1

Type RM Length L Ch R = 1 ,16.9    ,28.1,16.9,9.6
XS GIS Cut Line= 4
     1680491.341      252555.721      1680243.86       252932.93
     1680235.877       252980.83     1680381.571      253272.219
#Sta/Elev= 30
       0 1183.32     9.8 1180.82    58.8 1164.98    68.6 1160.79    78.5 1153.79
    88.3 1147.61    98.1 1143.12   137.3 1126.24   156.9 1120.68   176.5 1119.78
     255 1120.48   313.8 1118.51   372.7 1117.93   411.9 1115.42   470.6 1108.61
   474.4 1108.88   489.4 1110.26   499.7  1110.1   528.4 1113.91   557.2 1115.93
   614.7  1117.2   681.8 1117.15   700.9 1117.61   710.5 1118.99   720.1 1123.94
   739.2 1137.61   748.8 1143.36   758.4  1148.2     768 1151.67   825.5 1166.25
#Mann= 3 , 0 , 0
       0     .06       0   474.4    .045       0   489.4     .06       0
Bank Sta=474.4,489.4
XS Rating Curve= 0 ,0
Exp/Cntr=0.3,0.1

Chan Stop Cuts=-1
Use User Specified Reach Order=0
Composite Channel Slope=5